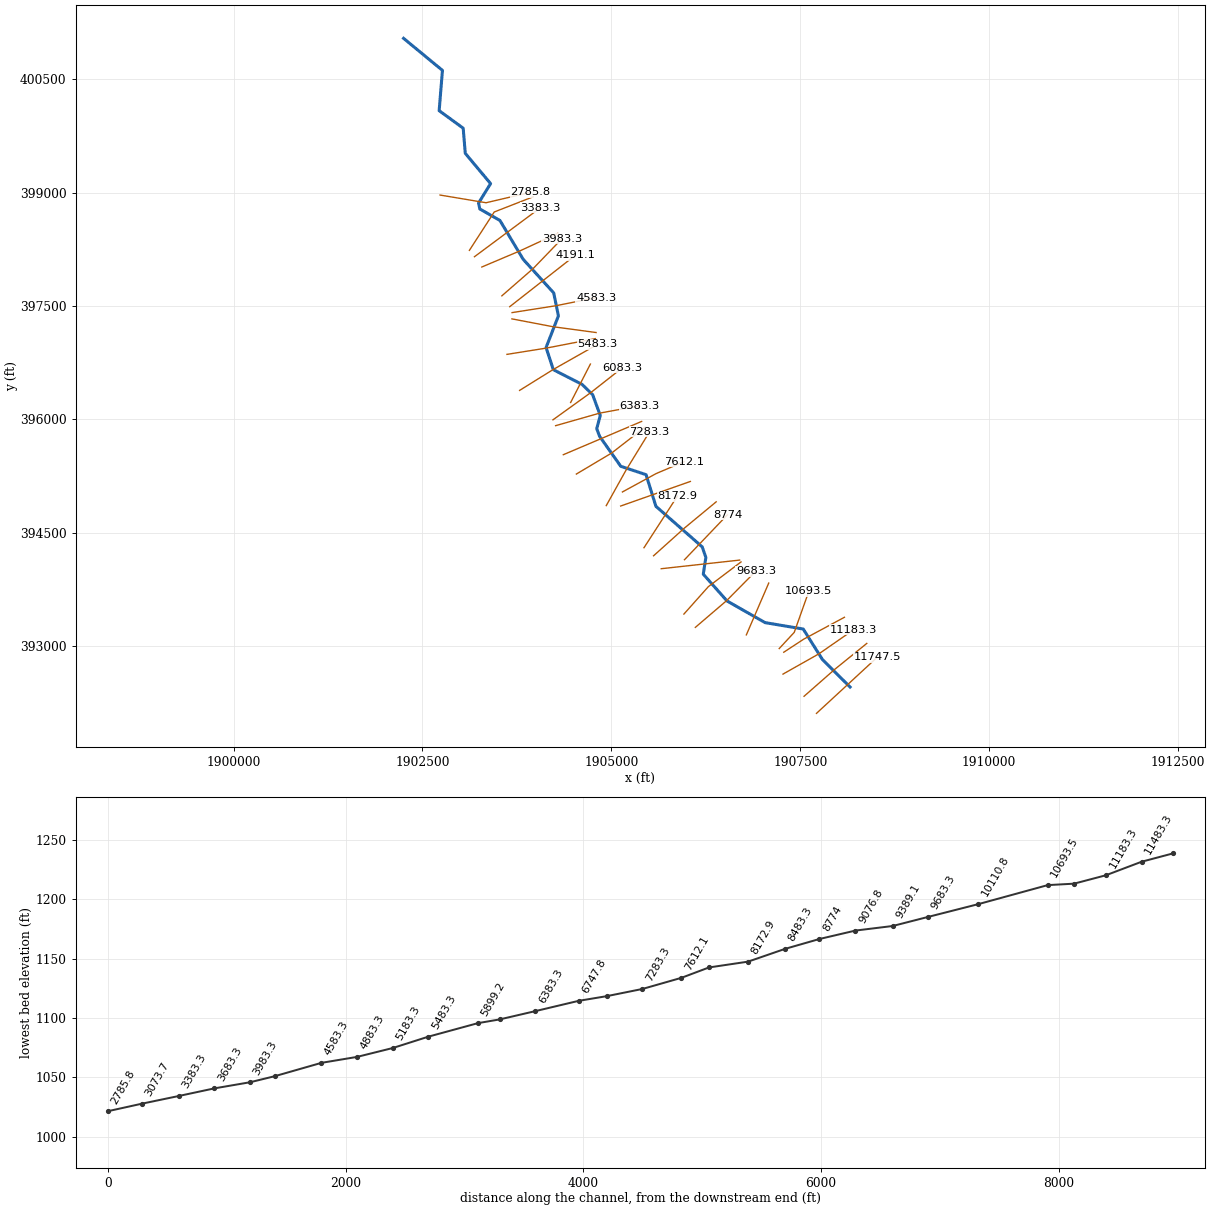
--- MulbrryFrk.prj (project) ---

Proj Title=MulbrryFrk
Current Plan=p01
Default Exp/Contr=0,0
English Units
Geom File=g01
Flow File=f01
Plan File=p01
BEGIN DESCRIPTION:
END DESCRIPTION:
DSS Export Rating Curves= 0
DSS Export Rating Curve Sorted= 0
DSS Export Volume Flow Curves= 0
DXF OffsetX= 0
DXF OffsetY= 0
DXF ScaleX= 0
DXF ScaleY= 0

--- MulbrryFrk.p01 (plan) ---

Plan Title=Floodplain
Program Version=4.00
Geom File=g01
Flow File=f01
K Sum by GR=0
Std Step Tol=0.01
Critical Tol=0.01
Num of Std Step Trials=20
Max Error Tol=0.3
Flow Tol Ratio=0.001
Split Flow NTrial=30
Split Flow Tol=0.02
Split Flow Ratio=0.02
Log Output Level=0
Friction Slope Method=1
Unsteady Friction Slope Method=2
Unsteady Bridges Friction Slope Method=1
Global Log Level=0
CheckData=False
Run HTab=0
Run UNet=0
Run PostProcess=0
UNET Theta=0
UNET Theta Warmup=0
UNET ZTol=0
UNET ZSATol=0
UNET MxIter=0
UNET MaxInSteps=0
UNET DtIC=0
UNET DtMin=0
UNET MaxCRTS=0
UNET WFStab=0
UNET SFStab=0
UNET WFX=0
UNET SFX=0
UNET DSS MLevel=0
UNET DZMax Abort=0
UNET Convert EG Bridges=0
UNET Use Existing IB Tables=0
UNET Froude Limit=0
UNET Froude Power=0
Write IC File=0
Echo Input=False
Echo Output=False
Write Detailed=0

--- MulbrryFrk.f01 (steady flow) ---

Flow Title=NFF Regression Equation
Program Version=4.00
Number of Profiles=1
Profile Names=P100yr
River Rch & RM=MulbrryFrk,Main      ,11747.5
626.2876
River Rch & RM=MulbrryFrk,Main      ,11483.3
626.2876
River Rch & RM=MulbrryFrk,Main      ,11183.3
936.0025
River Rch & RM=MulbrryFrk,Main      ,10110.8
979.3314
River Rch & RM=MulbrryFrk,Main      ,8172.9
1060.589
River Rch & RM=MulbrryFrk,Main      ,5899.2
1149.540
River Rch & RM=MulbrryFrk,Main      ,4191.1
1255.626
Boundary for River Rch & Prof#=MulbrryFrk,Main      ,1
Up Type=0
Dn Type=3
Dn Slope=0.020508

--- MulbrryFrk.g01 (geometry) ---

Geom Title=USGS 3m DEM
Program Version=4.10

River Reach=MulbrryFrk      ,Main
Reach XY= 30
     1908158.471      392459.411     1907792.152      392823.995
      1907538.68      393226.772     1907033.472      393311.842
     1906529.999        393598.3     1906215.763      393952.467
     1906250.044      394173.948     1906201.874      394313.578
     1905589.027      394850.036     1905458.819      395268.439
     1905123.749       395379.55     1904844.235      395775.383
     1904806.041      395876.078     1904852.916      396051.425
     1904752.222      396325.731     1904611.597      396462.883
     1904231.388      396657.328     1904135.902      396950.731
     1904299.096      397368.419     1904236.597      397672.953
     1903833.819      398115.661     1903524.791      398631.286
     1903259.166      398782.328     1903241.805      398860.453
      1903401.58      399118.473     1903066.458      399518.439
     1903038.964      399851.049     1902720.939      400083.111
     1902764.374      400615.661     1902250.172       401039.77

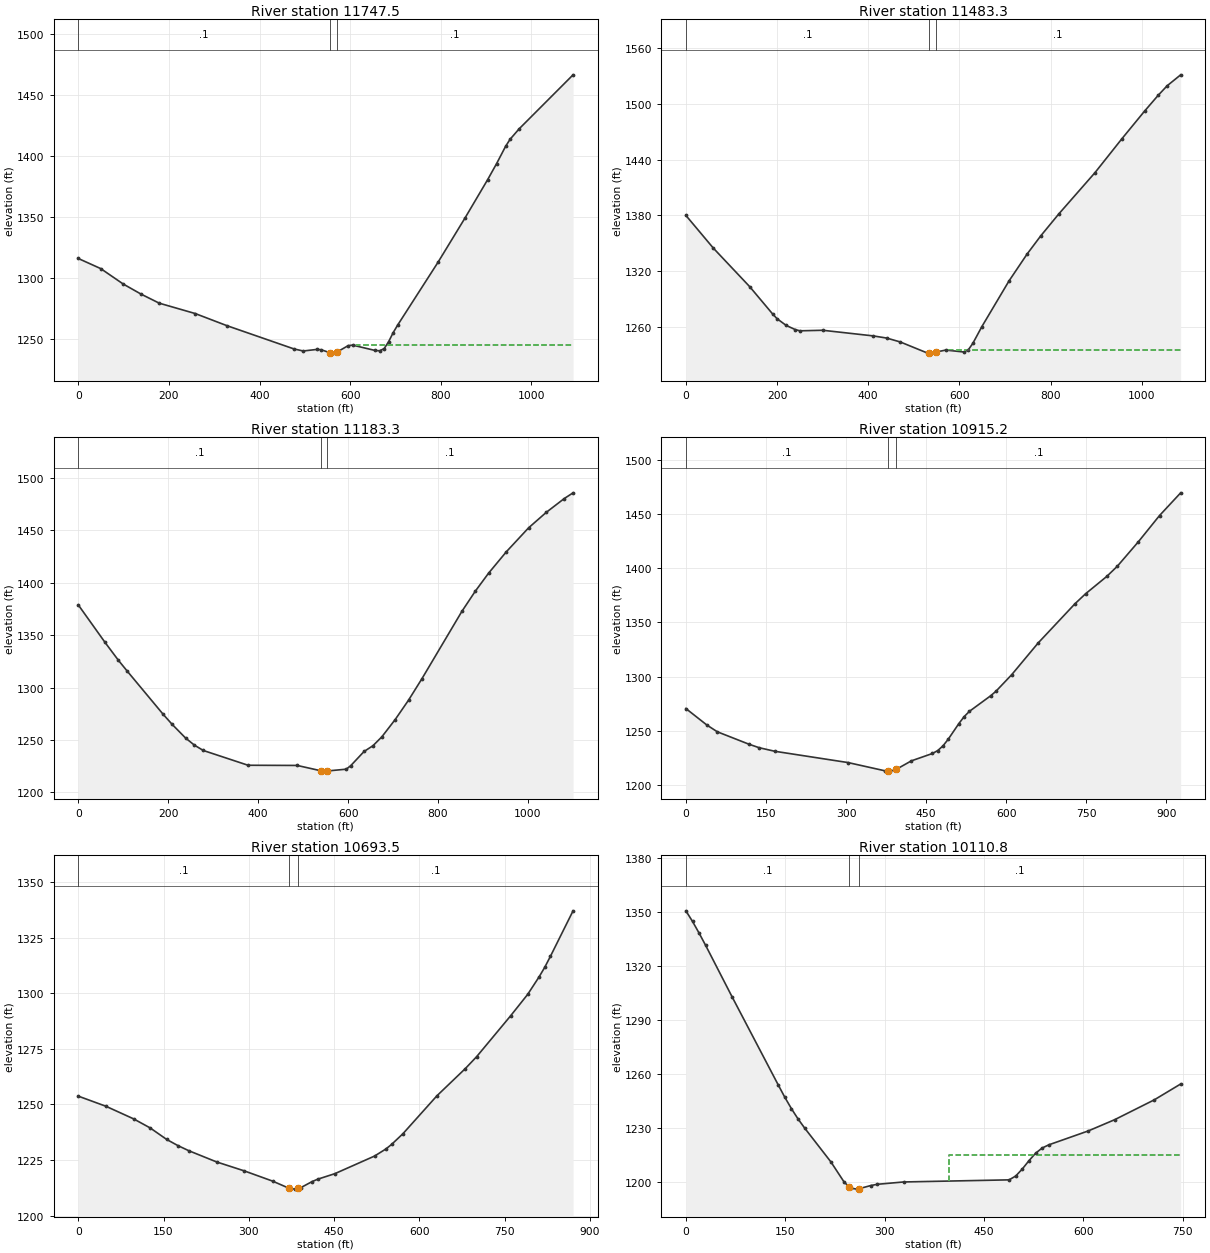
Type RM Length L Ch R = 1 ,11747.5 ,264.8,264.2,262.7
XS GIS Cut Line= 3
     1907713.832      392111.309     1908115.035       392481.65
     1908516.238      392851.991
#Sta/Elev= 30
       0  1316.1    49.6  1307.8    99.3 1295.16     139 1286.84   178.7 1279.51
   258.1 1271.02   327.6 1261.16   476.5    1242   496.4 1240.37   526.2 1241.63
   536.1 1241.39   555.3 1238.96   565.8 1238.62   570.3 1239.34   595.6 1244.74
   605.6 1245.17   655.2 1240.79   665.1 1240.56     675 1242.29     685 1248.02
   694.9 1255.33   704.8 1261.54   794.2 1313.15   853.8 1349.41   903.4 1380.57
   923.2 1393.72   943.1  1407.9     953 1413.66   972.9 1422.18    1092 1466.43
#Mann= 3 , 0 , 0
       0      .1       0   555.3    .045       0   570.3      .1       0
#XS Ineff= 2 , 0
                          612.75         1245.64
Permanent Ineff=
       F       F
Bank Sta=555.3,570.3
XS Rating Curve= 0 ,0
Exp/Cntr=0.3,0.1

Type RM Length L Ch R = 1 ,11483.3 ,304.7,299.9,298.2
XS GIS Cut Line= 3
     1907549.157      392337.145     1907955.455      392693.448
     1908379.237      393036.509
#Sta/Elev= 30
       0 1379.85      60 1344.75   140.1 1303.08   190.1 1273.87   200.2 1268.58
   220.2 1261.37   240.2 1256.88   250.2 1255.61   300.2  1256.2   410.3 1250.18
   440.3 1247.83   470.4 1243.61   530.4 1231.59   532.9 1231.61   547.9 1232.62
   570.1 1234.89   609.8 1232.82   619.7 1235.19   629.6 1242.12   649.4 1260.15
   708.9 1309.28   748.6 1338.24   778.3 1357.66     818 1381.34   897.3 1425.72
   956.8 1462.48  1006.3 1492.09  1036.1 1509.07  1055.9 1519.41  1085.6  1531.2
#Mann= 3 , 0 , 0
       0      .1       0   532.9    .045       0   547.9      .1       0
#XS Ineff= 2 , 0
                          574.61         1235.01
Permanent Ineff=
       F       F
Bank Sta=532.9,547.9
XS Rating Curve= 0 ,0
Exp/Cntr=0.3,0.1

Type RM Length L Ch R = 1 ,11183.3 ,268.5,268.1,265.4
XS GIS Cut Line= 3
     1907270.681      392630.741     1907746.709      392899.287
     1908201.619      393215.187
#Sta/Elev= 30
       0 1378.81    59.6 1342.96    89.4 1325.86   109.3  1315.4   188.8 1274.42
   208.7 1264.86   238.5 1251.85   258.4 1244.96   278.2  1239.9   377.6 1225.82
   486.9 1225.64   539.1  1220.6   546.6 1220.22   554.1 1220.37     596 1222.08
   605.9  1225.4   635.6 1238.98   655.3 1244.44   675.1 1252.92   704.8 1269.42
   734.5 1287.93   764.1 1308.26   853.1 1372.61   882.8 1391.78   912.5 1409.06
     952 1429.48  1001.5 1452.33    1041 1467.16  1080.6  1480.2  1100.4 1485.72
#Mann= 3 , 0 , 0
       0      .1       0   539.1    .045       0   554.1      .1       0
Bank Sta=539.1,554.1
XS Rating Curve= 0 ,0
Exp/Cntr=0.3,0.1

Type RM Length L Ch R = 1 ,10915.2 ,205.1,221.7,238.4
XS GIS Cut Line= 3
     1907281.128      392920.166      1907543.43      393091.979
     1908083.737      393382.384
#Sta/Elev= 30
       0 1270.77    39.2 1255.63    58.8 1249.38   117.6 1238.03   137.2 1234.71
   166.6 1231.42   303.8 1221.02   372.9 1213.44   379.1 1213.25   382.8 1213.14
   394.1 1214.77   422.4 1222.59     462 1229.39   471.9  1232.1   481.8 1236.46
   491.6 1242.59   511.4 1256.91   521.3  1263.3   531.2  1268.2   570.8 1282.45
   580.7 1286.58   610.4 1301.93   659.8 1331.04   729.1 1367.33   748.9 1376.48
   788.5 1392.41   808.2 1401.74   847.8 1424.37   887.4  1448.5     927  1469.4
#Mann= 3 , 0 , 0
       0      .1       0   379.1    .045       0   394.1      .1       0
Bank Sta=379.1,394.1
XS Rating Curve= 0 ,0
Exp/Cntr=0.3,0.1

Type RM Length L Ch R = 1 ,10693.5 ,584.2,582.7,581.1
XS GIS Cut Line= 3
     1907220.994      392969.037     1907419.534      393182.849
     1907613.492      393728.071
#Sta/Elev= 30
       0 1253.72    48.6 1249.17    97.3 1243.51   126.4 1239.44   155.6 1234.24
   175.1 1231.51   194.5 1229.18   243.2 1224.16   291.8 1220.14   341.7 1215.54
   370.8 1212.31   381.6 1211.92   385.8 1212.21   391.6  1212.6   411.5 1215.33
   421.5  1216.4   451.4 1218.87   521.3 1226.79   541.2 1229.97   551.2 1232.01
   571.2 1236.83     631 1253.88   680.9 1266.09   700.8 1271.44   760.7 1289.84
   790.6 1299.44   810.6 1307.27   820.6 1311.59   830.6 1316.53   870.5 1337.01
#Mann= 3 , 0 , 0
       0      .1       0   370.8    .045       0   385.8      .1       0
Bank Sta=370.8,385.8
XS Rating Curve= 0 ,0
Exp/Cntr=0.3,0.1

Type RM Length L Ch R = 1 ,10110.8 ,437.8,427.5,419.1
XS GIS Cut Line= 2
     1906785.733       393149.25     1907082.016      393834.977
#Sta/Elev= 30
       0 1350.84      10 1344.94    19.9 1338.46    29.9 1331.55    69.7    1303
   139.4 1253.94   149.4 1247.03   159.4 1240.68   169.3 1235.01   179.3 1229.92
   219.1    1211     239  1199.8   246.3 1197.34     249 1196.43     259 1195.93
   261.3 1196.14   278.9 1197.91   288.8 1198.61   328.7 1199.92     488 1201.09
     498 1203.24     508 1207.19   517.9 1211.74   527.9 1215.89   537.8  1218.8
   547.8 1220.57   607.6 1228.34   647.4 1234.59   707.2 1245.64     747 1254.46
#Mann= 3 , 0 , 0
       0      .1       0   246.3    .045       0   261.3      .1       0
#XS Ineff= 2 , 0
                          397.21         1214.94
Permanent Ineff=
       F       F
Bank Sta=246.3,261.3
XS Rating Curve= 0 ,0
Exp/Cntr=0.3,0.1

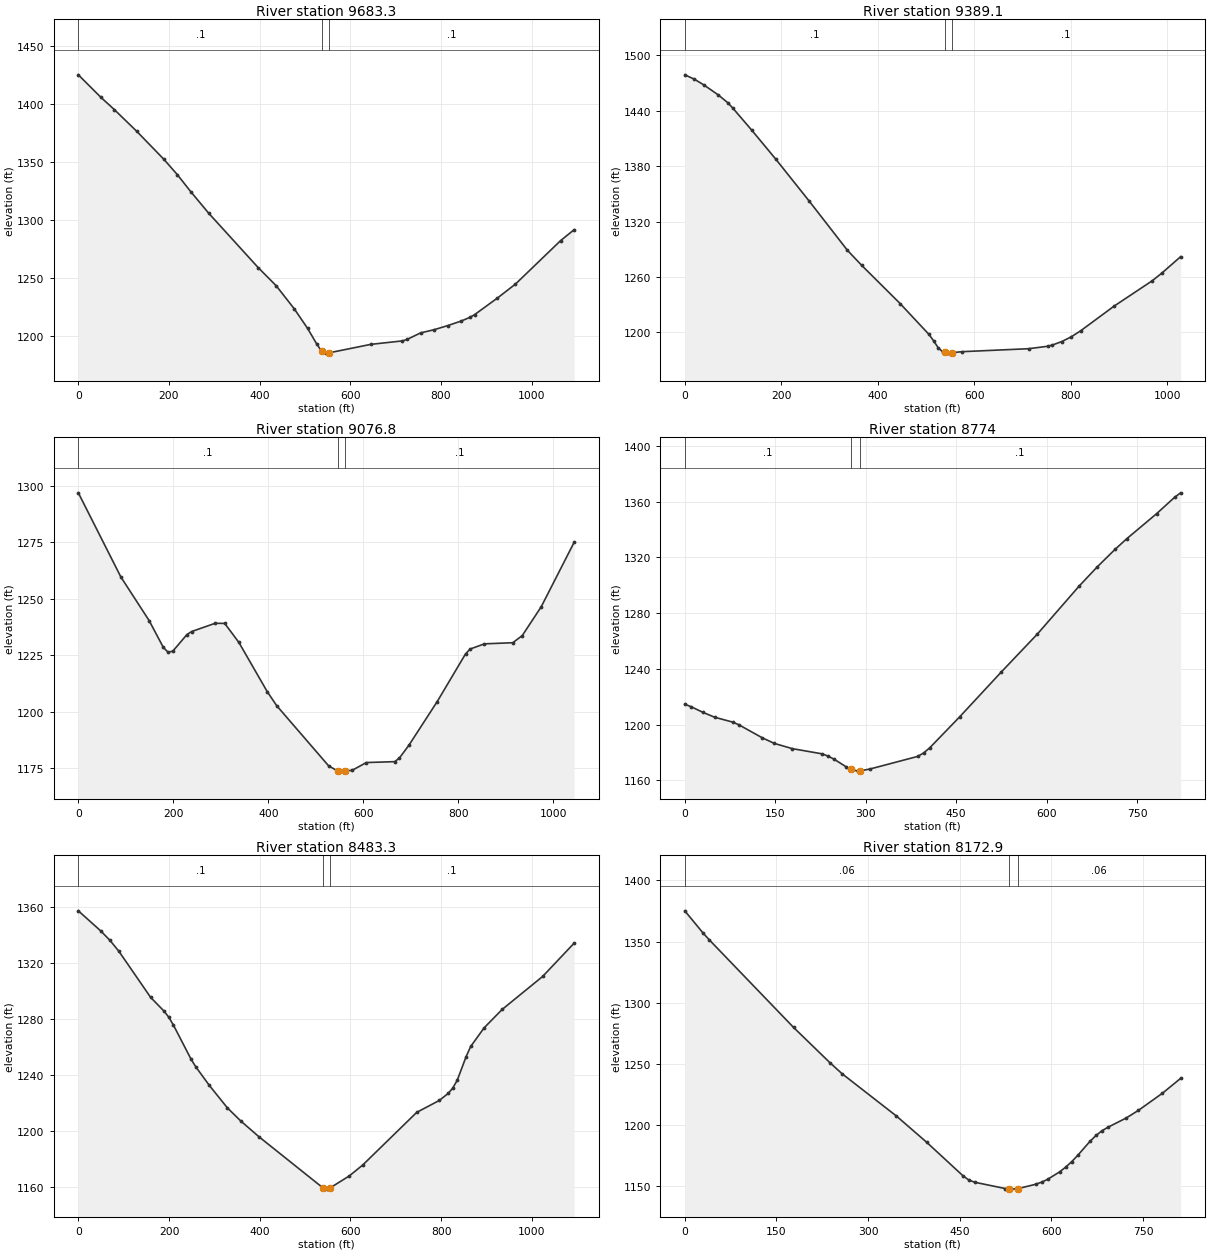
Type RM Length L Ch R = 1 ,9683.3  ,295.7,294.2,290.9
XS GIS Cut Line= 3
     1906110.978      393248.827     1906525.752       393603.27
     1906911.391       393993.07
#Sta/Elev= 30
       0 1425.38    49.6 1406.02    79.4 1395.36     129 1376.56   188.5 1352.52
   218.2 1339.28     248 1324.51   287.7 1305.84   396.8  1258.9   436.5 1243.25
   476.2 1223.42   505.9 1206.36   525.8 1193.02   535.7  1187.3   538.1 1186.75
   545.6 1185.04   553.1 1185.29   645.3 1192.61   715.1 1195.61     725 1196.82
     755  1202.5   784.9 1205.26   814.8 1208.79   844.7 1212.75   864.6 1216.05
   874.6 1218.38   924.4 1232.55   964.3 1244.64    1064 1282.21  1093.9 1291.64
#Mann= 3 , 0 , 0
       0      .1       0   538.1    .045       0   553.1      .1       0
Bank Sta=538.1,553.1
XS Rating Curve= 0 ,0
Exp/Cntr=0.3,0.1

Type RM Length L Ch R = 1 ,9389.1  ,324,312.2,300.5
XS GIS Cut Line= 3
     1905959.833      393424.869     1906283.274      393787.633
      1906715.48       394114.46
#Sta/Elev= 30
       0 1479.01    19.8  1474.3    39.7 1468.01    69.4 1457.24    89.3 1448.73
    99.2 1443.16   138.9 1418.98   188.5 1387.73   257.9 1342.21   337.2 1288.86
     367 1272.45   446.3 1231.25   505.7 1198.04   515.6 1191.04   525.4 1183.25
   535.3 1178.56   538.6  1178.2   545.1 1177.49   553.6 1177.96   574.7 1179.06
   712.6 1182.27     752  1184.9   761.9 1186.24   781.6 1190.03   801.3  1195.2
     821 1201.83     890 1228.42   968.8 1255.81   988.5 1263.98  1027.9 1281.99
#Mann= 3 , 0 , 0
       0      .1       0   538.6    .045       0   553.6      .1       0
Bank Sta=538.6,553.6
XS Rating Curve= 0 ,0
Exp/Cntr=0.3,0.1

Type RM Length L Ch R = 1 ,9076.8  ,287.2,302.8,318.4
XS GIS Cut Line= 2
     1905659.579      394024.611     1906697.153      394138.896
#Sta/Elev= 30
       0 1296.89    89.5 1259.64   149.1 1240.31     179 1228.42   188.9 1226.33
   198.8 1226.76   228.6 1234.12   238.6 1235.48   288.3 1239.14   308.2 1239.06
     338 1230.64   397.7 1208.85   417.5 1202.66   526.9    1176   545.6 1173.76
   556.7 1173.66   560.6 1173.66   576.6 1174.04   606.4 1177.46   666.1 1177.86
     676 1179.48   695.9 1185.12   755.6 1204.49   815.2 1225.59   825.1 1227.75
     855 1230.02   914.6 1230.52   934.5 1233.67   974.3 1246.38  1043.8    1275
#Mann= 3 , 0 , 0
       0      .1       0   545.6    .045       0   560.6      .1       0
Bank Sta=545.6,560.6
XS Rating Curve= 0 ,0
Exp/Cntr=0.3,0.1

Type RM Length L Ch R = 1 ,8774    ,292.4,290.6,288
XS GIS Cut Line= 2
     1905967.137      394143.478     1906535.312      394738.015
#Sta/Elev= 30
       0 1214.54     9.9 1212.92    29.7 1208.82    49.5 1205.24    79.3 1201.76
    89.2 1199.94   128.8 1190.42   148.6 1186.44   178.4  1182.7   227.9 1178.96
   237.8 1177.33   247.7  1175.1   267.5  1169.7   275.2 1167.98   287.3 1166.57
   290.2 1166.71   307.2  1168.1   386.4 1177.14   396.3 1179.68   406.2 1183.28
   455.8 1205.47   525.1 1237.77   584.6 1264.83   653.9 1299.26   683.7 1312.95
   713.4  1325.6   733.2 1333.38   782.7 1351.36   812.5 1363.08   822.4 1366.26
#Mann= 3 , 0 , 0
       0      .1       0   275.2    .045       0   290.2      .1       0
Bank Sta=275.2,290.2
XS Rating Curve= 0 ,0
Exp/Cntr=0.3,0.1

Type RM Length L Ch R = 1 ,8483.3  ,304.5,310.4,317.3
XS GIS Cut Line= 3
      1905558.27      394195.746     1905965.777      394561.576
      1906386.48       394909.15
#Sta/Elev= 30
       0 1357.49    49.8 1342.99    69.7 1336.36    89.6 1328.45   159.3 1295.58
   189.2  1285.6   199.1 1281.44   209.1 1276.04   248.9 1251.06   258.9 1245.83
   288.8 1232.51   328.6 1216.43   358.4 1206.95   398.3 1195.72   540.1 1158.94
   547.6 1158.22   555.1  1159.1   597.2 1167.61     627 1175.46   746.1 1213.17
   795.7 1221.68   815.5 1226.74   825.4 1230.48   835.4 1236.11   855.2 1253.18
   865.1 1260.35   894.9 1273.76   934.6  1286.9  1023.9 1310.53  1093.3 1334.37
#Mann= 3 , 0 , 0
       0      .1       0   540.1    .045       0   555.1      .1       0
Bank Sta=540.1,555.1
XS Rating Curve= 0 ,0
Exp/Cntr=0.3,0.1

Type RM Length L Ch R = 1 ,8172.9  ,343.5,328.7,313.9
XS GIS Cut Line= 2
     1905431.334       394302.31     1905872.449      394983.454
#Sta/Elev= 30
       0 1375.18    29.7 1357.13    39.6 1351.68   178.1 1279.74   237.5 1250.95
   257.3 1241.95   346.4 1207.28   395.9 1185.82   455.2 1158.45   465.1 1154.85
     475 1153.07   524.5 1147.96   530.2 1147.69   534.4 1147.49   545.2 1147.89
     574 1151.42   583.9 1153.17   593.8  1155.5   613.6 1161.66   623.5 1165.54
   633.4 1170.04   643.3 1175.24   663.1 1186.54     673 1191.41   682.8 1195.25
   692.8 1198.18   722.4 1205.67   742.2 1211.84   781.8 1225.98   811.5 1238.11
#Mann= 3 , 0 , 0
       0     .06       0   530.2    .045       0   545.2     .06       0
Bank Sta=530.2,545.2
XS Rating Curve= 0 ,0
Exp/Cntr=0.3,0.1

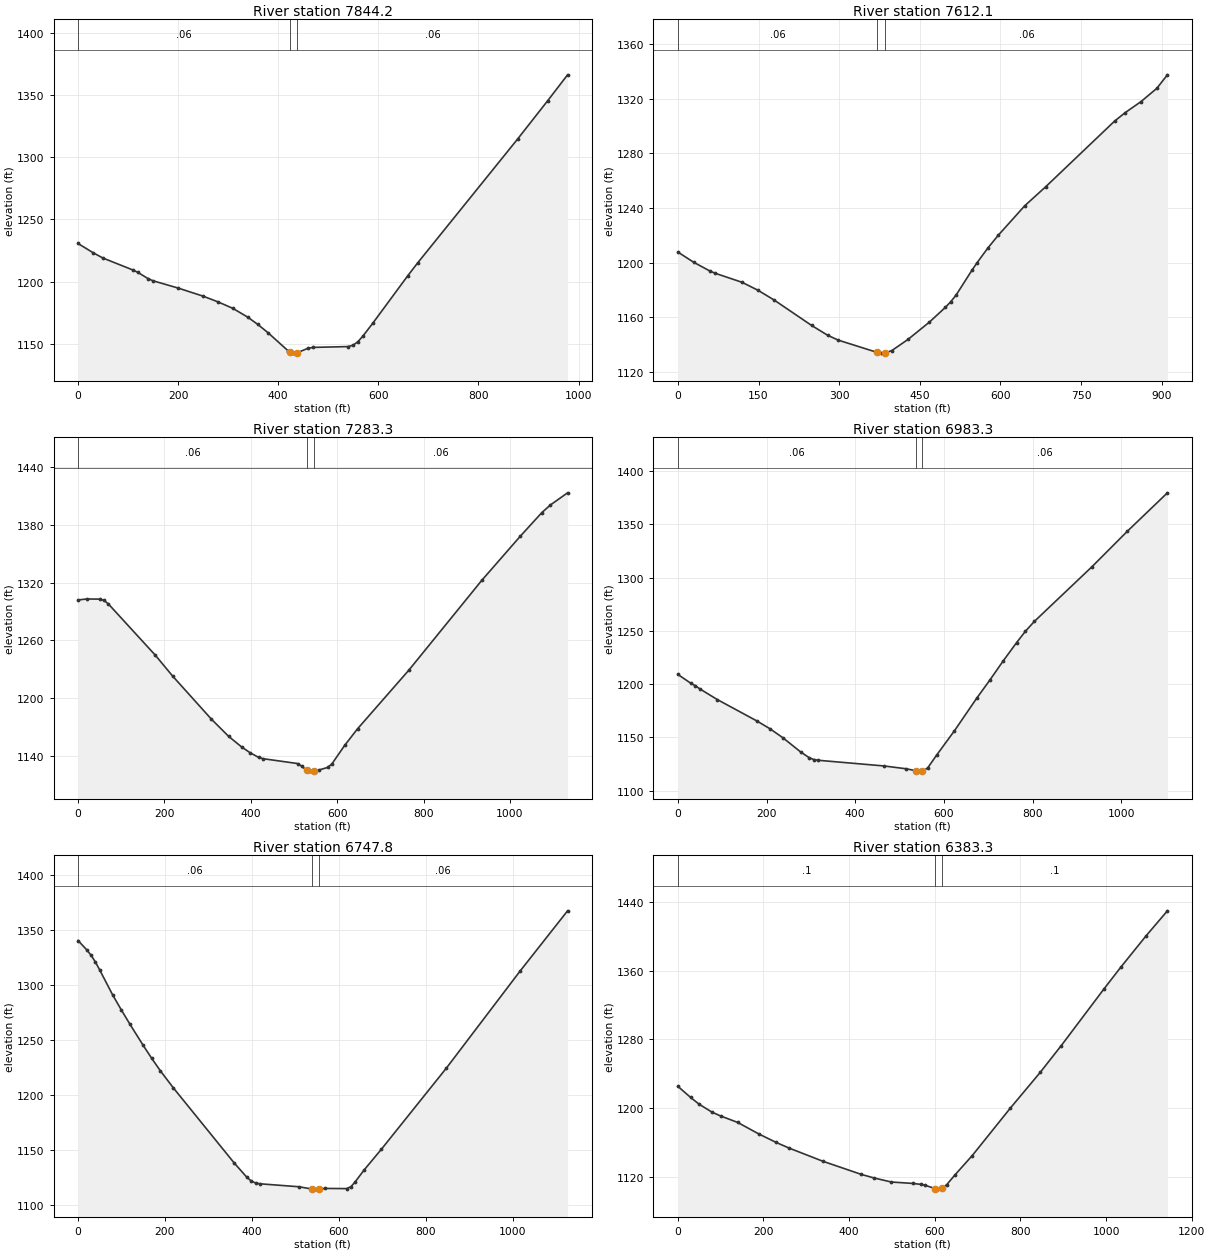
Type RM Length L Ch R = 1 ,7844.2  ,228,232,235.9
XS GIS Cut Line= 2
     1905122.578       394853.64     1906045.026       395178.94
#Sta/Elev= 30
       0 1230.66    29.9  1223.3    49.9 1218.94   109.8 1209.36   119.8  1207.4
   139.7 1202.51   149.7 1200.72   199.6 1194.91   249.5 1188.41   279.5 1183.79
   309.4 1178.55   339.4 1171.42   359.3 1165.61   379.3  1159.1   419.2 1144.65
   423.5 1143.77   429.2  1142.6   438.5    1143   459.1 1146.44   469.1  1147.2
     539 1147.85     549 1148.83   558.9 1151.66   568.9 1156.15   588.9 1166.61
   658.7 1204.68   678.7 1215.13   878.3 1314.56   938.2 1345.24   978.1 1366.12
#Mann= 3 , 0 , 0
       0     .06       0   423.5    .045       0   438.5     .06       0
Bank Sta=423.5,438.5
XS Rating Curve= 0 ,0
Exp/Cntr=0.3,0.1

Type RM Length L Ch R = 1 ,7612.1  ,315.7,328.3,339.9
XS GIS Cut Line= 3
      1905146.06      395039.962     1905591.629      395282.792
     1905962.433      395440.517
#Sta/Elev= 30
       0 1207.77    29.8 1200.22    59.7 1193.89    69.6 1192.23   119.4 1185.65
   149.2  1179.8   179.1 1172.68   248.8 1154.09   278.6 1146.92   298.5 1143.33
     371 1134.35   378.1 1133.86     386  1134.1     398 1135.76   427.8 1143.83
   467.6 1156.48   497.5 1167.32   507.4 1171.42   517.3 1176.22   546.8 1194.41
   556.6 1200.05   576.2 1210.57   595.9 1220.07     645 1241.58   684.4 1255.64
   812.1 1303.49   831.8 1309.68   861.3 1317.78   890.7 1327.48   910.4 1337.36
#Mann= 3 , 0 , 0
       0     .06       0     371    .045       0     386     .06       0
Bank Sta=371,386
XS Rating Curve= 0 ,0
Exp/Cntr=0.3,0.1

Type RM Length L Ch R = 1 ,7283.3  ,311.8,300.1,292
XS GIS Cut Line= 3
     1904932.163       394859.19     1905194.125      395329.314
     1905505.773      395836.668
#Sta/Elev= 30
       0 1301.97    19.9 1302.97    49.8 1302.85    59.8 1301.56    69.8 1298.09
   179.4 1244.49   219.3 1222.93     309  1178.3   348.8 1160.52   378.7 1149.62
   398.6 1143.52   418.6 1138.64   428.6 1137.37   508.3 1132.35   518.2 1129.54
   528.2 1125.73   530.7 1125.42   538.2 1124.48   545.7  1124.7     558 1125.66
   577.9  1128.3   587.8 1131.91   617.6 1151.27   647.3 1168.38   766.4 1229.36
   935.1 1322.38  1024.4  1368.2  1074.1 1392.58  1093.9 1400.49  1133.6 1413.06
#Mann= 3 , 0 , 0
       0     .06       0   530.7    .045       0   545.7     .06       0
Bank Sta=530.7,545.7
XS Rating Curve= 0 ,0
Exp/Cntr=0.3,0.1

Type RM Length L Ch R = 1 ,6983.3  ,238.7,235.4,229.4
XS GIS Cut Line= 3
     1904536.317      395276.623     1905003.559      395554.832
     1905446.064      395898.525
#Sta/Elev= 30
       0 1209.14    29.7 1200.73    39.6 1198.53    49.4 1195.63      89 1185.56
     178 1165.54   207.6 1158.22   237.3 1149.61   276.8 1136.46   296.6 1130.91
   306.5 1129.32   316.4 1128.61   464.7 1123.28   514.1 1120.67   536.3 1118.87
   543.8 1118.42   551.3 1118.61   553.8 1118.67   563.8 1121.67   583.8 1133.54
   623.8 1156.28   673.9 1186.75   703.9 1203.98   733.9 1221.91   763.9 1238.93
   783.9 1249.67   803.9 1258.81     934 1310.18    1014 1343.54  1104.1  1379.5
#Mann= 3 , 0 , 0
       0     .06       0   536.3    .045       0   551.3     .06       0
Bank Sta=536.3,551.3
XS Rating Curve= 0 ,0
Exp/Cntr=0.3,0.1

Type RM Length L Ch R = 1 ,6747.8  ,367.3,364.4,359.4
XS GIS Cut Line= 2
     1904364.179      395532.737     1905400.645      395972.901
#Sta/Elev= 30
       0 1340.64    19.9 1332.25    29.9 1327.29    39.9 1321.14    49.8 1313.95
    79.7 1291.14    99.6 1277.52   119.6 1264.39   149.5 1245.53   169.4 1233.53
   189.3 1222.18   219.2 1206.63   358.7 1138.56   388.6 1125.17   398.6 1121.88
   408.6 1120.06   418.5 1119.35   508.2 1116.65   538.7 1114.57   548.1  1114.5
   553.7 1114.69     568 1115.14   617.8 1114.97   627.8 1116.71   637.8 1121.24
   657.7 1131.74   697.6 1150.67     847 1224.42  1016.4 1312.62  1126.1 1367.65
#Mann= 3 , 0 , 0
       0     .06       0   538.7    .045       0   553.7     .06       0
Bank Sta=538.7,553.7
XS Rating Curve= 0 ,0
Exp/Cntr=0.3,0.1

Type RM Length L Ch R = 1 ,6383.3  ,292.2,300,310.9
XS GIS Cut Line= 3
     1904262.115      395916.524     1904847.092      396083.041
      1905373.26      396179.967
#Sta/Elev= 30
       0 1225.39    29.9 1212.43    49.8 1204.54    79.8 1195.37    99.7 1190.95
   139.6 1183.42   189.4 1169.91   229.3 1160.21   259.2 1153.69     339 1138.18
   428.7 1122.92   458.6 1118.75   498.5 1114.12   548.4 1112.47   568.3 1111.33
   578.3 1110.17   600.7 1106.51   608.2 1105.84   615.7 1106.76   618.1 1107.06
     628 1111.12   647.8 1122.76   687.5 1144.89   776.6 1200.17     846 1241.49
   895.5 1272.86   994.6 1338.34  1034.2 1363.83  1093.7 1400.57  1143.2 1429.47
#Mann= 3 , 0 , 0
       0      .1       0   600.7    .045       0   615.7      .1       0
Bank Sta=600.7,615.7
XS Rating Curve= 0 ,0
Exp/Cntr=0.3,0.1

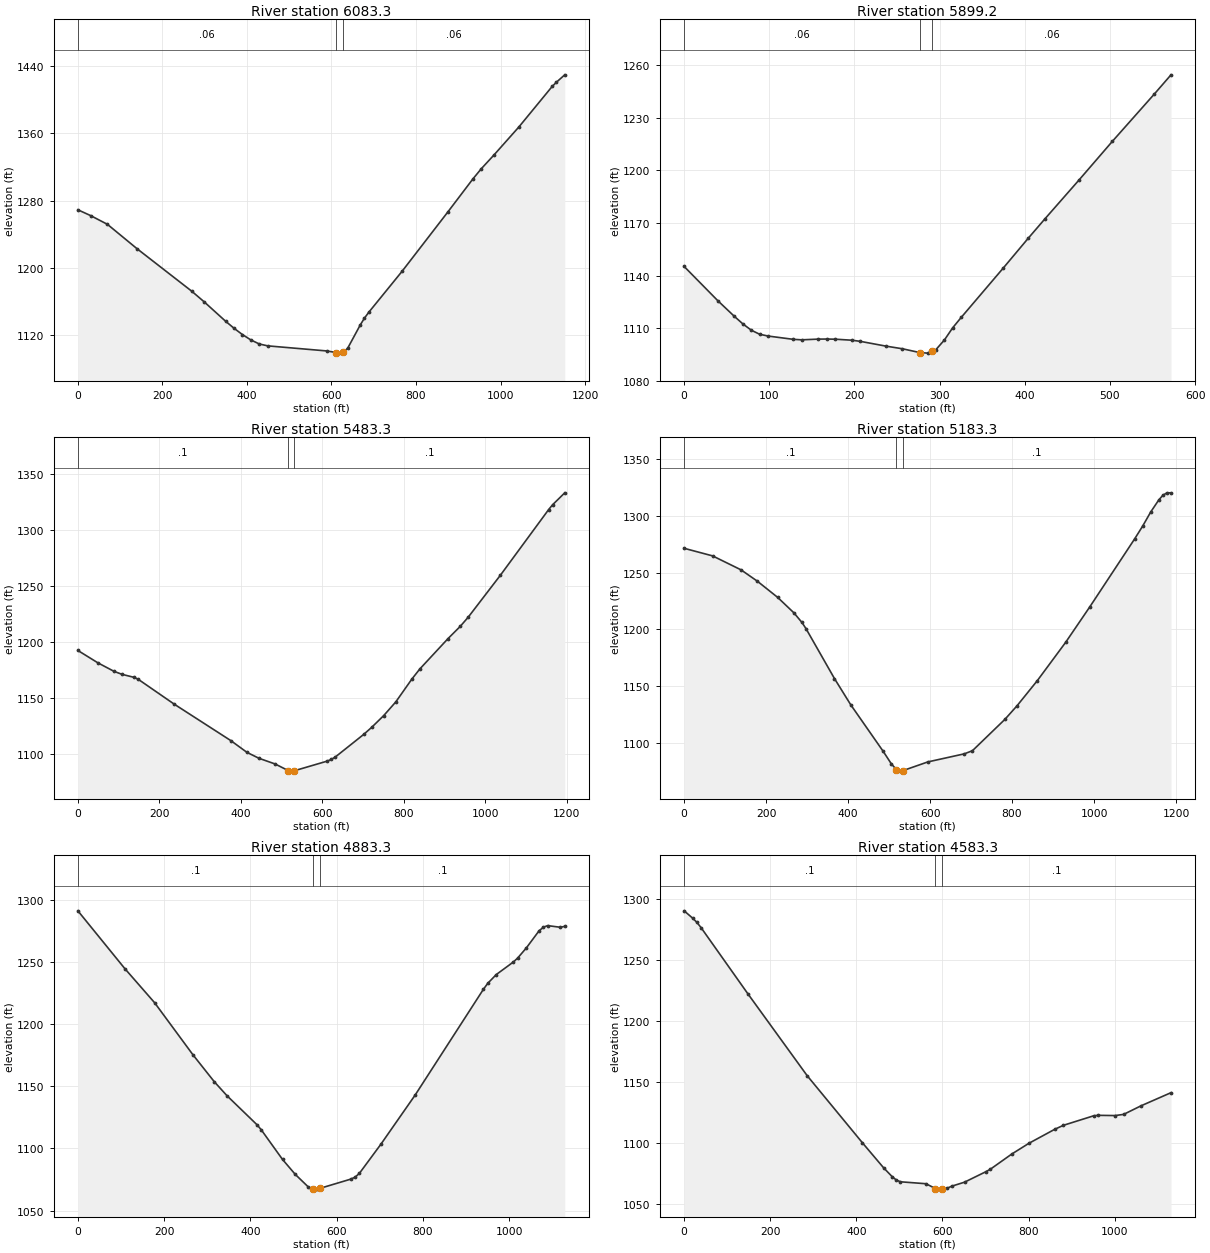
Type RM Length L Ch R = 1 ,6083.3  ,173.5,184.2,193.9
XS GIS Cut Line= 3
     1904226.804      395993.714     1904728.946      396355.354
     1905148.172      396684.746
#Sta/Elev= 30
       0  1269.2    29.9 1262.35    69.9 1251.93   139.7 1223.06   269.5 1172.42
   299.4 1159.55   349.3 1136.86   369.3 1128.48   389.2 1120.95   409.2 1114.57
   429.2 1109.74   449.1  1107.5   588.9 1101.45   611.3 1099.56   618.8 1098.86
   626.3 1099.67   628.7 1099.93   638.6 1104.89   668.2  1132.4     678  1140.4
   687.9 1147.18   766.9 1195.98   875.5  1266.7   934.8 1305.97   954.5 1317.98
   984.1  1334.1  1043.4  1367.6  1122.3 1415.83  1132.2 1420.78    1152  1429.6
#Mann= 3 , 0 , 0
       0     .06       0   611.3    .045       0   626.3     .06       0
Bank Sta=611.3,626.3
XS Rating Curve= 0 ,0
Exp/Cntr=0.3,0.1

Type RM Length L Ch R = 1 ,5899.2  ,428.1,415.8,402.7
XS GIS Cut Line= 2
     1904460.906      396223.184     1904722.062      396731.752
#Sta/Elev= 30
       0 1145.16    39.4 1125.69    59.1 1116.63      69 1112.36    78.9 1108.77
    88.7 1106.46    98.6 1105.44   128.1 1103.57     138 1103.28   157.7 1103.69
   167.6 1103.73   177.4 1103.64   197.1 1103.06     207  1102.4   236.6 1099.72
   256.3 1098.18   276.4 1096.04   285.8 1095.69   291.4 1096.83   295.7 1097.71
   305.6 1103.18   315.4 1110.18   325.3 1116.04   374.6 1144.18   404.1 1161.29
   423.8 1172.42   463.3  1194.3   502.7  1216.5     552 1243.52   571.7 1254.56
#Mann= 3 , 0 , 0
       0     .06       0   276.4    .045       0   291.4     .06       0
Bank Sta=276.4,291.4
XS Rating Curve= 0 ,0
Exp/Cntr=0.3,0.1

Type RM Length L Ch R = 1 ,5483.3  ,309,300,292.7
XS GIS Cut Line= 3
     1903785.479      396383.064     1904230.185        396659.6
     1904814.479      396990.303
#Sta/Elev= 30
       0 1192.07    49.4 1180.96    88.9  1173.4   108.7 1170.72   138.3 1168.03
   148.2 1166.31   237.1 1143.99   375.5 1111.57     415  1101.1   444.6 1095.79
   484.2 1090.72   516.2 1084.86   523.7 1084.34   531.2 1084.66   612.5 1093.33
   622.4 1094.84   632.3 1097.07   701.4 1117.07   721.1 1123.41   750.8 1133.96
   780.4 1146.16   819.9 1166.58   839.6 1175.66   908.7 1202.72   938.4 1213.51
   958.1 1221.78  1037.1 1259.24  1155.6 1317.89  1165.4 1322.22  1195.1 1332.82
#Mann= 3 , 0 , 0
       0      .1       0   516.2    .045       0   531.2      .1       0
Bank Sta=516.2,531.2
XS Rating Curve= 0 ,0
Exp/Cntr=0.3,0.1

Type RM Length L Ch R = 1 ,5183.3  ,307.8,300,292.6
XS GIS Cut Line= 3
     1903618.283      396859.771     1904137.238      396942.333
     1904787.458      397068.106
#Sta/Elev= 30
       0 1271.53    69.4 1264.84   138.8 1252.51   178.5 1242.52     228 1228.24
   267.7 1214.58   287.5 1206.01   297.4 1200.54   366.8 1156.49   406.5 1133.33
   485.8 1092.15   505.6 1081.14     518  1076.1   525.5 1074.76     533 1075.11
   594.7 1082.91   683.6 1090.03   703.4  1092.8   782.5 1120.45   812.1 1132.44
   861.6 1154.64   930.8  1188.5   990.1 1220.03  1098.8 1279.68  1118.6  1291.1
  1138.3  1303.6  1158.1  1314.3    1168 1318.35  1177.9 1320.52  1187.8 1320.51
#Mann= 3 , 0 , 0
       0      .1       0     518    .045       0     533      .1       0
Bank Sta=518,533
XS Rating Curve= 0 ,0
Exp/Cntr=0.3,0.1

Type RM Length L Ch R = 1 ,4883.3  ,292.2,300,307.5
XS GIS Cut Line= 3
     1903683.855      397329.245      1904227.46      397225.404
     1904797.631      397148.693
#Sta/Elev= 30
       0 1290.99   108.7 1244.59   177.9 1217.12   266.8 1175.25   316.2 1153.63
   345.9 1142.29   415.1 1119.09     425 1115.03   474.4 1091.15     504 1079.12
   533.7  1069.2   545.9 1067.47   553.4 1067.29   560.9 1067.88   632.8 1075.34
   642.7 1076.93   652.6 1079.96   702.2 1103.26   781.6 1142.76   940.3 1228.02
   950.2 1232.71     970 1239.78  1009.7 1249.88  1019.6 1253.06  1039.5  1261.1
  1069.2 1274.95  1079.2 1277.83  1089.1  1279.1  1118.8 1277.76  1128.7 1278.53
#Mann= 3 , 0 , 0
       0      .1       0   545.9    .045       0   560.9      .1       0
Bank Sta=545.9,560.9
XS Rating Curve= 0 ,0
Exp/Cntr=0.3,0.1

Type RM Length L Ch R = 1 ,4583.3  ,380.6,392.2,402.7
XS GIS Cut Line= 3
     1903685.704      397412.132     1904269.907      397503.644
     1904798.879      397610.304
#Sta/Elev= 30
       0 1290.23    19.7 1284.25    29.6 1280.78    39.4 1276.44   147.8 1222.41
   285.8  1155.2   413.9 1100.34   463.2 1079.82   482.9 1072.62   492.8 1069.75
   502.6 1068.29   561.8  1066.7   583.8 1062.76   591.3 1062.28   598.8  1062.3
   611.3 1063.04   621.3 1064.65   651.3 1067.97   701.2 1076.59   711.2 1078.54
   761.2 1091.05   801.2 1099.87   861.1 1111.32   881.1 1114.56   951.1 1122.32
   961.1 1122.73    1001 1122.53    1021 1123.51    1061 1130.46    1131 1141.28
#Mann= 3 , 0 , 0
       0      .1       0   583.8    .045       0   598.8      .1       0
Bank Sta=583.8,598.8
XS Rating Curve= 0 ,0
Exp/Cntr=0.3,0.1

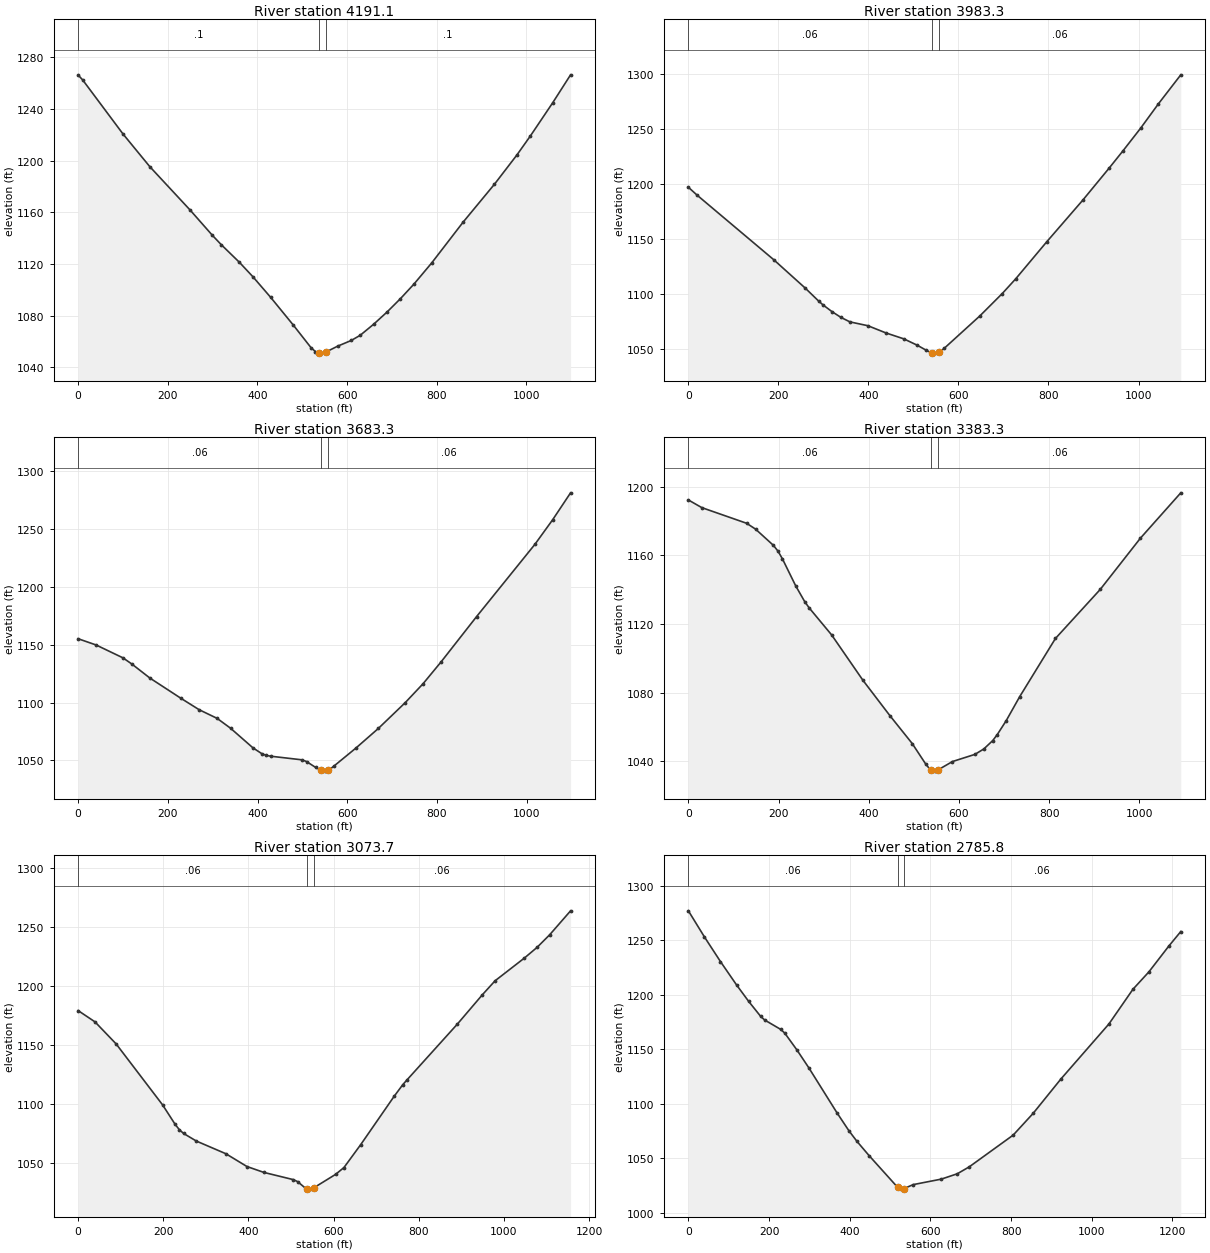
Type RM Length L Ch R = 1 ,4191.1  ,206.6,207.8,211
XS GIS Cut Line= 2
     1903654.858      397490.409     1904519.629      398168.066
#Sta/Elev= 30
       0 1266.08      10 1262.36    99.9  1220.6   159.8 1195.28   249.7 1161.74
   299.6  1142.1   319.6 1134.81   359.6 1121.35   389.5 1110.27   429.5  1094.2
   479.4 1073.01   519.4 1055.35   529.4 1052.25   537.7 1051.24   539.3 1051.05
   552.7 1051.87   579.3 1056.49   609.3 1060.83   629.2 1064.82   659.2 1073.36
   689.2 1082.84   719.1 1093.17   749.1 1104.39     789 1120.87     859 1152.38
   928.9 1181.69   978.8 1204.22  1008.8 1218.89  1058.7  1244.6  1098.7 1266.27
#Mann= 3 , 0 , 0
       0      .1       0   537.7    .045       0   552.7      .1       0
Bank Sta=537.7,552.7
XS Rating Curve= 0 ,0
Exp/Cntr=0.3,0.1

Type RM Length L Ch R = 1 ,3983.3  ,307.1,299.9,291.4
XS GIS Cut Line= 3
     1903550.786      397634.099     1903964.284      397994.245
     1904343.244       398386.74
#Sta/Elev= 30
       0 1196.72    19.9 1189.37   189.4 1130.94   259.2 1105.21   289.1 1093.39
   299.1 1089.79     319 1083.68     339 1078.41   358.9 1074.35   398.8 1070.87
   438.7 1064.34   478.6 1058.92   508.5 1053.12   528.4 1048.56   538.4 1046.55
   540.8 1046.41   548.4 1045.95   555.8 1046.79   558.3 1047.07   568.2 1050.26
   647.6 1079.81   697.1 1100.03   726.9 1113.37   796.3 1147.26   875.7 1184.79
   935.2 1214.38     965 1229.61  1004.7 1250.45  1044.3 1272.64  1093.9 1298.94
#Mann= 3 , 0 , 0
       0     .06       0   540.8    .045       0   555.8     .06       0
Bank Sta=540.8,555.8
XS Rating Curve= 0 ,0
Exp/Cntr=0.3,0.1

Type RM Length L Ch R = 1 ,3683.3  ,294.7,300.1,304.8
XS GIS Cut Line= 3
     1903285.641      398015.212      1903791.72      398229.338
     1904289.466       398459.57
#Sta/Elev= 30
       0 1155.12      40 1149.74    99.9 1138.62   119.9 1133.24   159.9 1121.18
   229.8 1103.53   269.8 1093.83   309.7 1086.39   339.7 1077.87   389.7 1060.91
   409.6 1055.84   419.6 1054.37   429.6 1053.67   499.6 1050.53   509.6 1048.98
   529.5 1043.99     542 1041.52   549.5  1040.8     557  1041.6   559.5 1041.87
   569.5 1044.91   619.3 1060.72   669.2 1077.62     729 1099.85   768.9 1116.23
   808.8 1134.94   888.5 1174.33  1018.2 1236.56    1058  1257.9  1097.9 1281.13
#Mann= 3 , 0 , 0
       0     .06       0     542    .045       0     557     .06       0
Bank Sta=542,557
XS Rating Curve= 0 ,0
Exp/Cntr=0.3,0.1

Type RM Length L Ch R = 1 ,3383.3  ,301.5,309.6,317.7
XS GIS Cut Line= 3
     1903187.939      398151.103     1903626.236      398476.697
     1904064.533      398802.291
#Sta/Elev= 30
       0  1192.3    29.8 1187.84     129 1178.74   148.9 1175.34   188.6 1165.86
   198.6 1162.55   208.5 1158.04   238.2 1142.18   258.1 1133.03     268 1129.41
   317.7  1113.7   387.2 1087.24   446.7 1066.75   496.4 1050.44   526.2 1038.55
   536.1 1035.31   538.5 1035.08     546 1034.37   553.5 1035.07   585.7 1039.96
   635.4 1044.12   655.2 1047.29     675 1052.18     685 1055.65   704.8 1063.75
   734.6 1077.68     814 1111.63   913.3 1140.18  1002.6 1170.09    1092 1196.46
#Mann= 3 , 0 , 0
       0     .06       0   538.5    .045       0   553.5     .06       0
Bank Sta=538.5,553.5
XS Rating Curve= 0 ,0
Exp/Cntr=0.3,0.1

Type RM Length L Ch R = 1 ,3073.7  ,314,287.8,261.6
XS GIS Cut Line= 3
     1903121.027      398235.631     1903449.879      398743.115
     1903964.128      398943.651
#Sta/Elev= 30
       0 1179.33    39.6 1169.76    89.2 1151.08   198.3 1099.38     228 1082.75
   237.9 1078.24   247.8  1075.1   277.6 1068.69     347 1057.93   396.5 1047.08
   436.2 1042.09   505.6 1035.95   515.5 1034.27   535.3 1028.29   538.7 1028.16
   545.2 1027.91   553.7 1029.07   604.7 1040.42   624.4 1046.23   663.9 1065.74
   742.7 1106.86   762.4 1116.44   772.3  1120.5   890.6 1167.82   949.7 1192.85
   979.3 1204.61  1048.3 1223.93  1077.8  1232.9  1107.4 1243.56  1156.7 1263.96
#Mann= 3 , 0 , 0
       0     .06       0   538.7    .045       0   553.7     .06       0
Bank Sta=538.7,553.7
XS Rating Curve= 0 ,0
Exp/Cntr=0.3,0.1

Type RM Length L Ch R = 1 ,2785.8  ,286,300.9,315.8
XS GIS Cut Line= 3
      1902732.77      398967.027     1903341.445      398865.293
     1903929.158      399002.759
#Sta/Elev= 30
       0 1276.86    39.8 1252.92    79.6 1230.28   119.4  1208.9   149.3 1193.86
   179.2 1180.02   189.1  1176.7   228.9 1168.08   238.9 1164.68   268.8 1149.38
   298.6 1132.82   368.3 1091.61   398.1 1075.02     418 1065.33   447.9 1052.32
     519 1023.09   527.5 1021.54     534 1021.98   557.4 1025.69     627 1030.72
   666.6 1035.62   696.3 1041.99   805.1 1071.08   854.6 1091.02   923.8 1122.71
  1042.6  1173.1    1102 1204.87  1141.5  1220.8    1191 1244.53  1220.7 1257.86
#Mann= 3 , 0 , 0
       0     .06       0     519    .045       0     534     .06       0
Bank Sta=519,534
XS Rating Curve= 0 ,0
Exp/Cntr=0.3,0.1