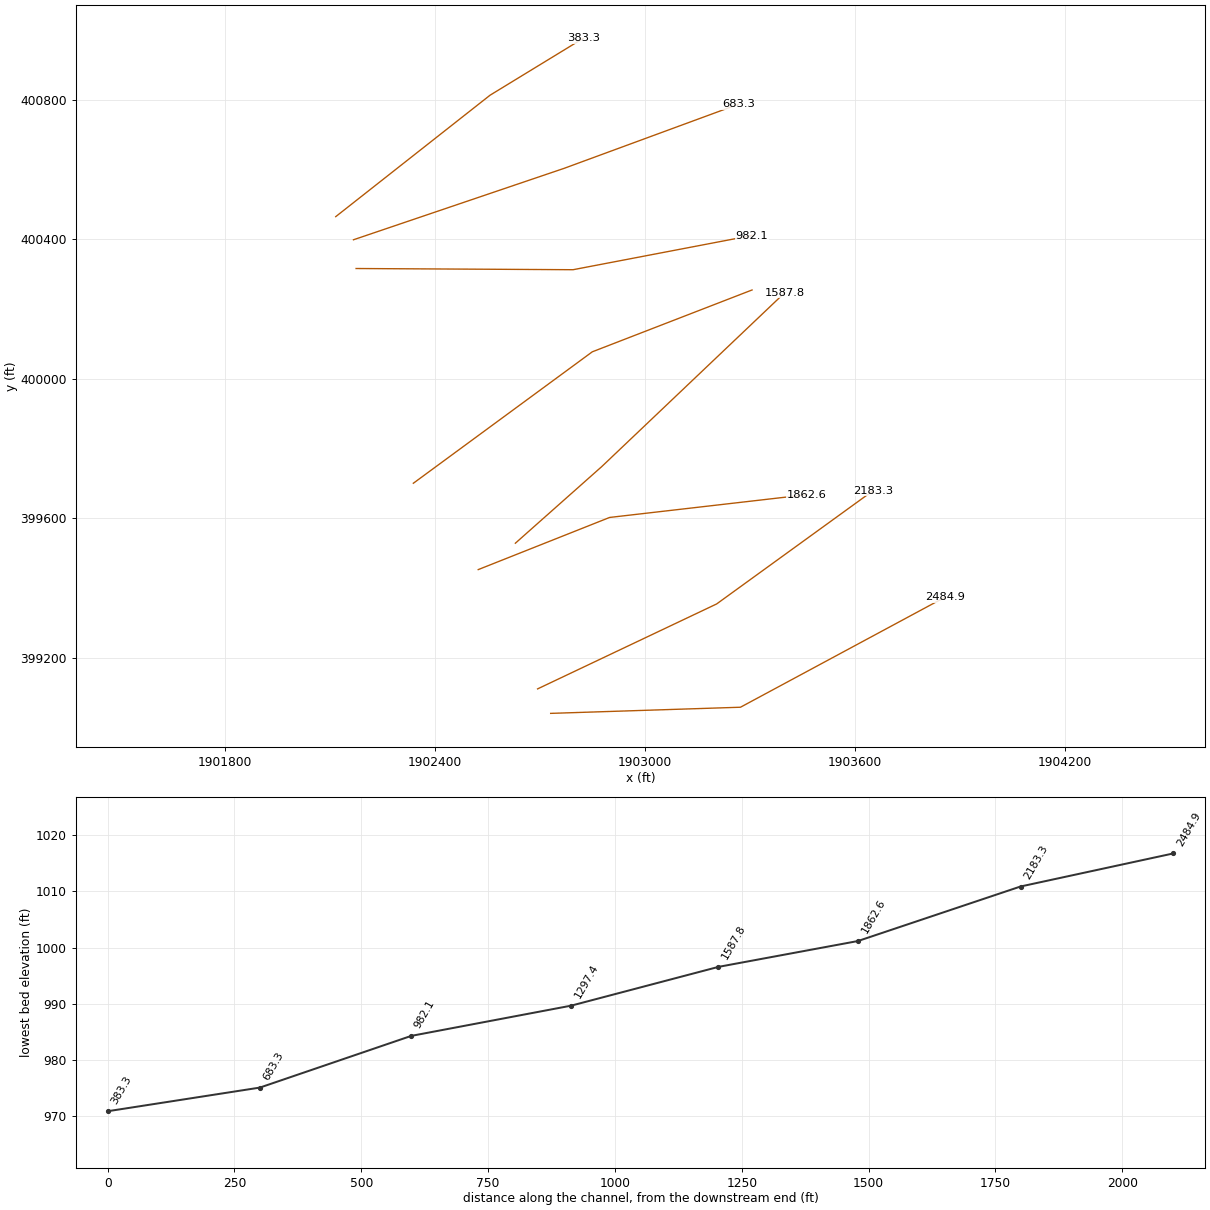
HEC-RAS study MulbrryFrk.prj: MulbrryFrk

--- MulbrryFrk.g01 (geometry) --- (continued)

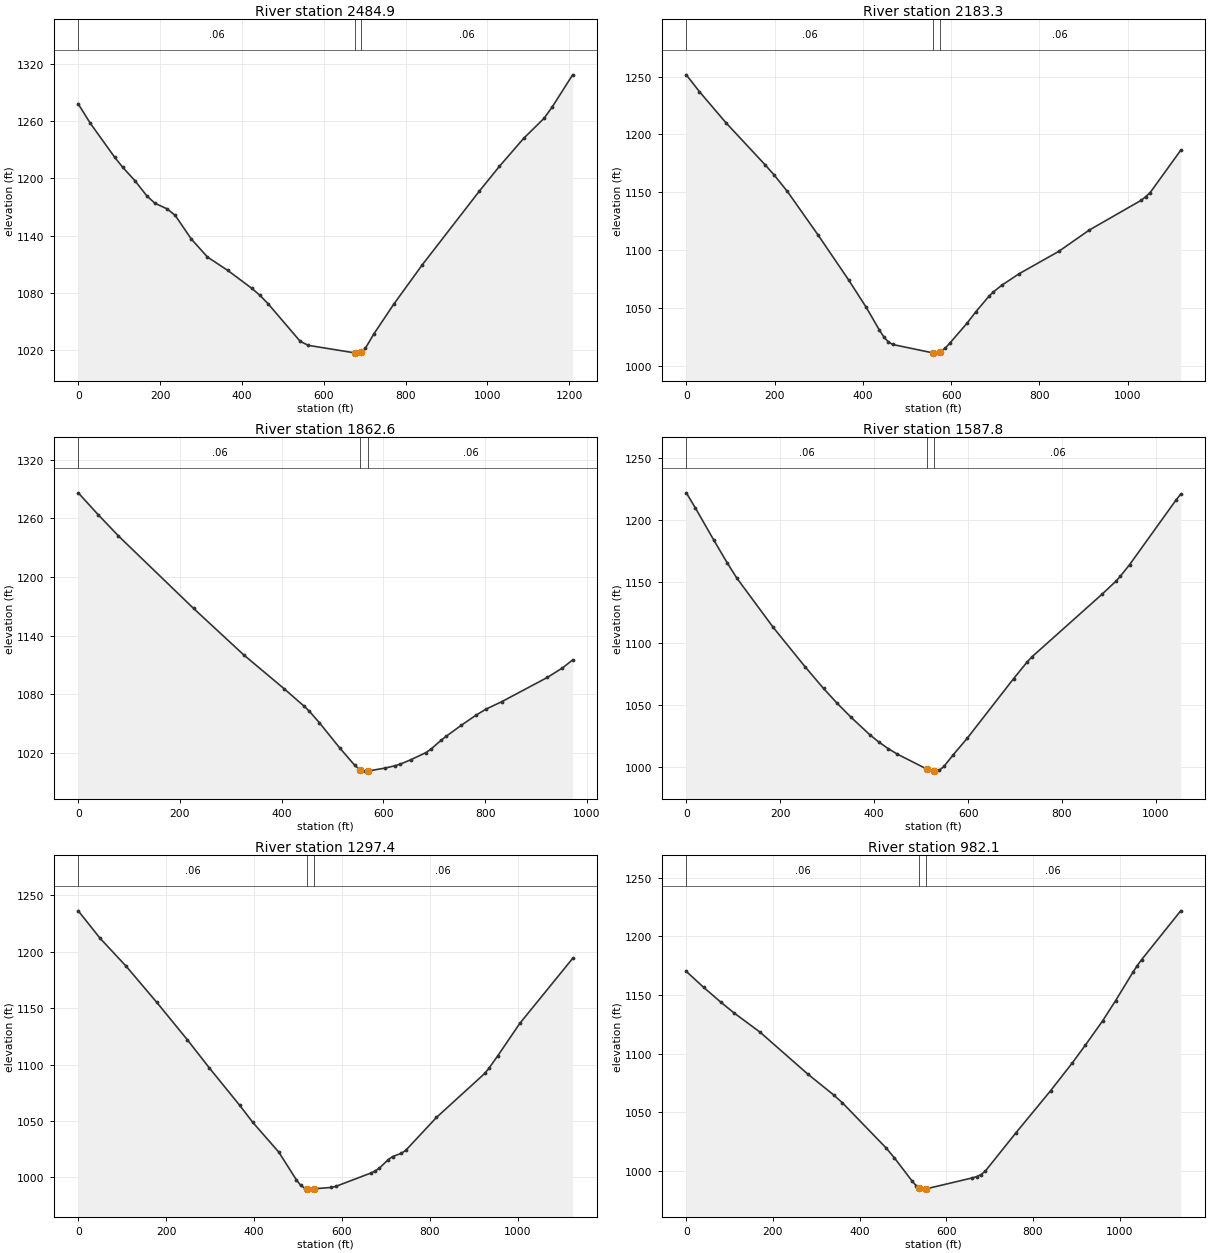
Type RM Length L Ch R = 1 ,2484.9  ,302.9,301.4,304.4
XS GIS Cut Line= 3
     1902730.153      399041.652      1903272.72      399059.252
     1903858.457      399375.026
#Sta/Elev= 30
       0 1278.06    29.6 1257.72    88.8 1222.29   108.6 1211.68   138.2 1197.73
   167.8 1181.52   187.5 1173.89   217.1 1168.01   236.9 1161.21   276.4 1136.34
   315.8 1117.51   365.2 1103.52   424.4 1084.61   444.2 1077.26   463.9 1068.55
   542.8 1028.92   562.7 1024.86   677.2 1016.88   681.9 1016.72   692.2 1017.82
   701.8 1021.81   721.6 1036.28   771.3 1068.16   840.8 1109.33   979.8 1186.38
  1029.5 1212.69  1089.1 1242.21  1138.8 1263.14  1158.6 1275.07  1208.3  1308.6
#Mann= 3 , 0 , 0
       0     .06       0   677.2    .045       0   692.2     .06       0
Bank Sta=677.2,692.2
XS Rating Curve= 0 ,0
Exp/Cntr=0.3,0.1

Type RM Length L Ch R = 1 ,2183.3  ,327.7,320.6,309.1
XS GIS Cut Line= 3
     1902692.778      399111.785     1903204.619      399355.124
     1903652.388      399680.062
#Sta/Elev= 30
       0 1251.48    29.8 1236.92    89.5 1210.17     179 1173.48   198.9 1164.92
   228.7 1150.76   298.3  1113.1   367.9 1074.01   407.7 1050.35   437.5  1030.7
   447.4 1024.89   457.4  1020.7   467.3 1018.33   559.2    1011   566.7 1010.84
   574.2 1011.79   586.5 1015.17   596.4 1019.22   635.9 1036.68   655.7 1046.54
   685.3 1059.87   695.2 1063.61   714.9  1069.6   754.4 1079.59   843.4 1098.74
   912.5 1117.16  1031.1 1143.13    1041 1146.23  1050.8 1149.64    1120 1186.24
#Mann= 3 , 0 , 0
       0     .06       0   559.2    .045       0   574.2     .06       0
Bank Sta=559.2,574.2
XS Rating Curve= 0 ,0
Exp/Cntr=0.3,0.1

Type RM Length L Ch R = 1 ,1862.6  ,260.5,274.9,289.2
XS GIS Cut Line= 3
     1902523.073      399453.495     1902898.803      399602.946
      1903462.86      399668.108
#Sta/Elev= 30
       0  1286.1    39.4 1263.59    78.9 1242.03   226.8 1167.73   325.5 1120.14
   404.4 1085.72   444.2 1067.63   454.2 1062.61   474.1 1050.79   513.9 1025.07
   543.8 1007.07   553.8 1002.61   554.9 1002.45   563.8 1001.15   569.9  1001.3
   603.6 1004.28   623.5 1006.76   633.5  1008.4   653.4 1012.67   683.3 1020.02
   693.2  1023.5   713.2 1032.59   723.1 1036.67     753 1048.01   782.9 1058.68
   802.8  1064.9   832.7 1072.22   922.4 1097.05   952.2 1106.81   972.2 1114.99
#Mann= 3 , 0 , 0
       0     .06       0   554.9    .045       0   569.9     .06       0
Bank Sta=554.9,569.9
XS Rating Curve= 0 ,0
Exp/Cntr=0.3,0.1

Type RM Length L Ch R = 1 ,1587.8  ,293.1,290.3,287.6
XS GIS Cut Line= 3
     1902629.247       399529.13     1902876.658      399749.051
     1903399.155      400246.658
#Sta/Elev= 30
       0 1222.04    19.5 1209.65    58.4 1183.81    87.6 1164.98   107.1 1153.21
     185 1113.04   253.1 1081.01   292.1 1063.58   321.3 1051.47   350.8 1040.18
   390.3 1026.18   410.1 1020.06   429.9 1014.81   449.6 1010.29   513.4  997.98
   528.4  996.58   528.7  996.56   538.6  997.15   548.5 1000.37   568.2 1009.75
   597.9 1023.12   696.7 1071.44   726.4 1085.32   736.3  1089.3   884.5 1139.69
   914.2 1150.26   924.1 1154.44   943.8 1163.83  1042.7 1216.24  1052.6 1220.93
#Mann= 3 , 0 , 0
       0     .06       0   513.4    .045       0   528.4     .06       0
Bank Sta=513.4,528.4
XS Rating Curve= 0 ,0
Exp/Cntr=0.3,0.1

Type RM Length L Ch R = 1 ,1297.4  ,329.7,315.2,300.8
XS GIS Cut Line= 3
      1902337.63      399700.909     1902849.168      400077.406
      1903305.81      400254.564
#Sta/Elev= 30
       0 1236.35    49.6 1212.04   109.2 1187.16   178.6 1155.26   248.1 1122.13
   297.7 1097.38   367.2 1064.05     397 1048.92   456.5 1022.39   496.2     998
   506.1  993.04   516.1  990.33   520.8  990.02     526  989.67   535.8  989.97
   575.6  991.16   585.5  992.02   665.1 1003.82   675.1 1005.62   685.1 1008.27
   705.1 1015.69   715.1  1018.5   735.1 1021.41   745.1    1024   815.1  1053.2
     925 1092.22     935 1097.06     955 1108.08    1005  1136.7    1125 1194.17
#Mann= 3 , 0 , 0
       0     .06       0   520.8    .045       0   535.8     .06       0
Bank Sta=520.8,535.8
XS Rating Curve= 0 ,0
Exp/Cntr=0.3,0.1

Type RM Length L Ch R = 1 ,982.1   ,290.9,298.6,306.8
XS GIS Cut Line= 3
     1902173.945      400316.025     1902794.188      400312.599
     1903305.417      400410.578
#Sta/Elev= 30
       0 1170.06      40 1156.48      80 1143.68     110 1134.68   170.1 1118.24
   280.1 1082.54   340.1 1064.65   360.2 1057.97   460.2 1019.76   480.2 1010.96
   520.2  991.58   530.2   987.3   537.4  985.46   540.2  984.74   550.2   984.3
   552.4  984.46   660.3  993.91   670.3  995.05   680.3  996.78   690.3  999.85
   760.4 1032.27   840.5 1068.26   890.5 1091.92   920.6 1107.04   960.6 1127.87
   990.6 1145.15  1030.7 1169.42  1040.7  1175.1  1050.7 1180.15  1140.8 1221.76
#Mann= 3 , 0 , 0
       0     .06       0   537.4    .045       0   552.4     .06       0
Bank Sta=537.4,552.4
XS Rating Curve= 0 ,0
Exp/Cntr=0.3,0.1

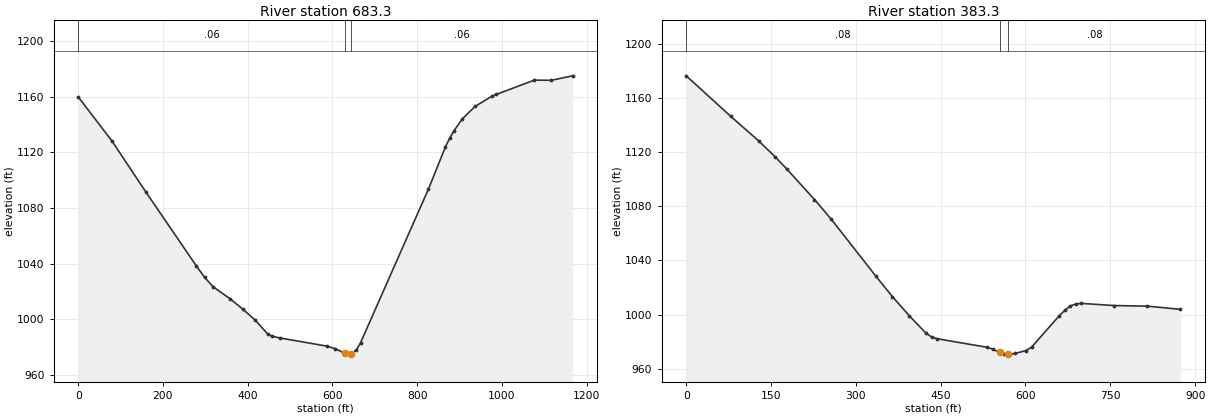
Type RM Length L Ch R = 1 ,683.3   ,292.3,300,304.2
XS GIS Cut Line= 3
      1902166.39      400398.356     1902768.993      400603.125
     1903266.352      400786.361
#Sta/Elev= 30
       0 1159.72    79.6 1128.06   159.1 1091.71   278.4 1038.55   298.3  1030.2
   318.2 1023.45     358 1014.92   387.8 1007.54   417.7  999.54   447.5  989.41
   457.4  987.93   477.3  986.65   586.7  980.85   606.6     979   628.9  975.72
   636.4  975.11   643.9  975.46   656.4  978.06   666.4  983.41   826.5 1093.61
   866.5  1123.8   876.5 1130.03   886.5 1135.33   906.5 1143.98   936.5 1152.88
   976.5 1160.26   986.5 1161.51  1076.5 1171.78  1116.5 1171.65  1166.5 1174.87
#Mann= 3 , 0 , 0
       0     .06       0   628.9    .045       0   643.9     .06       0
Bank Sta=628.9,643.9
XS Rating Curve= 0 ,0
Exp/Cntr=0.3,0.1

Type RM Length L Ch R = 1 ,383.3   ,376.5,383.3,393
XS GIS Cut Line= 3
     1902115.681      400464.575     1902556.978      400812.563
     1902823.205      400975.417
#Sta/Elev= 30
       0 1176.22    78.9 1146.28   128.2 1128.18   157.8 1116.29   177.5 1107.65
   226.8 1084.98   256.4  1070.5   335.2 1028.51   364.8 1013.28   394.4  999.24
     424  986.39   433.8  983.62   443.7  982.27   532.4  975.94   542.3  974.57
   554.5  972.13     562  970.99   569.5  970.93   571.8  970.91   581.5  971.39
     601  973.57   610.8  976.07   659.5  999.12   669.3 1003.12     679 1006.48
   688.8 1007.84   698.5 1008.35     757 1006.74   815.6 1006.31   874.1 1003.93
#Mann= 3 , 0 , 0
       0     .08       0   554.5    .045       0   569.5     .08       0
Bank Sta=554.5,569.5
XS Rating Curve= 0 ,0
Exp/Cntr=0.3,0.1

Chan Stop Cuts=-1
Use User Specified Reach Order=0
Composite Channel Slope=5